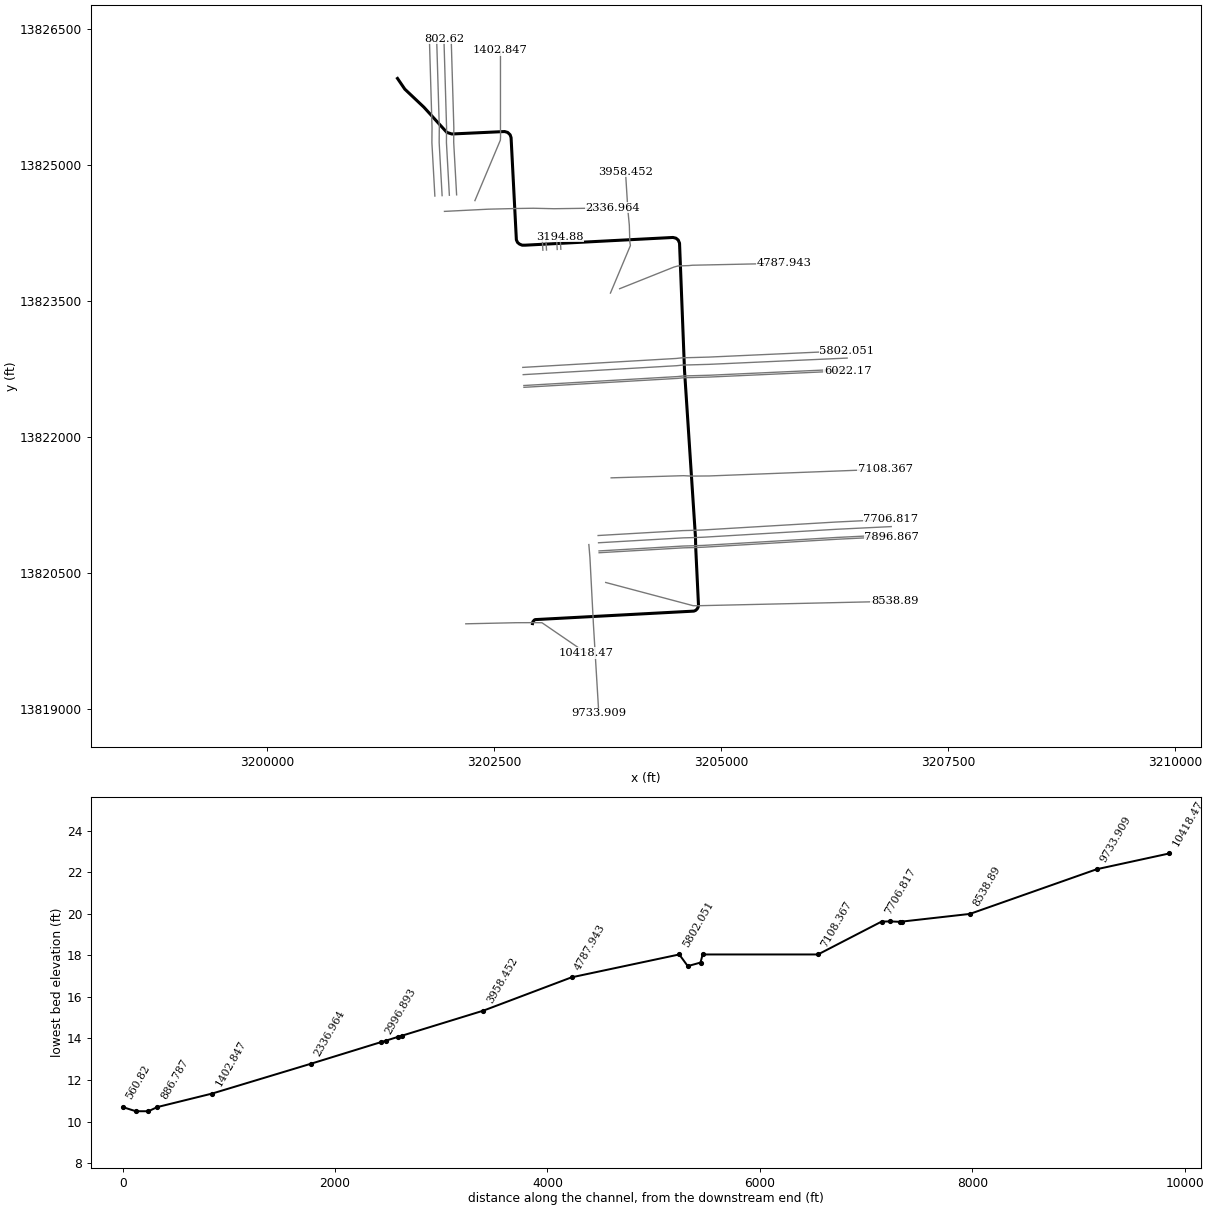
--- G104-08-00.prj (project) ---

Proj Title=G104-08-00
Current Plan=p02
Default Exp/Contr=.3,.1
English Units
Geom File=g01
Flow File=f01
Flow File=f02
Plan File=p01
Plan File=p02
Y Axis Title=Elevation
X Axis Title(PF)=Main Channel Distance
X Axis Title(XS)=Station
BEGIN DESCRIPTION:
HCFCD MODEL SUMMARY METADATA
The purpose of this summary is to document the high points of hydrologic and hydraulic models filed within the HCFCD Model and Map Management (M3) system.  The document includes references to the project that prompted the creation or update of the model.
DESCRIPTION OF PROJECT:
The following model was the hydraulic model which represented the effective condition of Harris County's watersheds.
PURPOSE OF PROJECT:
Development of effective models to support the National Flood Insurance Program.
HCFCD Watershed Unit ID: G
M3 Study Identifier: 2007_Effective_G
Engineer: HCFCD
Project Name: EffectiveFEMA Study for watershed San Jancinto River (G)
Study Completion Date: 6/18/2007
FEMA Case Number: [No Data]
FEMA Approval Date: [No Date in Database]
Vertical Datum: NAVD 1988
Datum Note: 2001 ADJ
HYDRAULICS
HCFCD Unit No.:  G104-08-00
Hydraulic Program Name: HEC-RAS
Hydraulic Program Version: 3.0.1
Steady Hydraulic Model: Yes
Unsteady Hydraulic Model: No
Update 1: The effective FEMA hydraulic model for unit number G104-08-00 has been updated by FEMA LOMR 16-06-0467P with an effective date of 11/18/2016.
END DESCRIPTION:
DSS Export Rating Curves= 0
DSS Export Rating Curve Sorted= 0
DSS Export Volume Flow Curves= 0
DXF OffsetX= 0
DXF OffsetY= 0
DXF ScaleX= 1
DXF ScaleY= 10

--- G104-08-00.p02 (plan) ---

Plan Title=FEMA Effective Floodway 2016
Version=Version 3.0.1  May 2012
Short Identifier=Eff+LOMR FW
Geom File=g01
Flow File=f02
Subcritical Flow
K Sum by GR= 0
Std Step Tol= 0.01
Critical Tol= 0.01
Num of Std Step Trials= 20
Max Error Tol= 0.3
Flow Tol Ratio= 0.001
Split Flow NTrial= 30
Split Flow Tol= 0.02
Split Flow Ratio= 0.02
Log Output Level= 0
Friction Slope Method= 0
Unsteady Friction Slope Method= 2
Secant Critical Depth
Global Vel Dist= 0 , 0 , 0
Global Log Level= 0
CheckData=True
Encroach Param=-1 ,0,0, 2
Encroach River=G104-08-00
Encroach Reach=G104-08-00_0006
Encroach Node=10418.47
       1 4975.16 5002.59
Encroach Node=9733.909
       1 4980.41 5019.59
Encroach Node=8538.89
       1 4983.48 5016.52
Encroach Node=7896.867
       1 4979.07 5020.93
Encroach Node=7876.866
       1 4979.07 5020.93
Encroach Node=7831
       1 4979.07 5020.93
Encroach Node=7786.862
       1 4979.07 5020.93
Encroach Node=7706.817
       1 4979.07 5020.93
Encroach Node=7108.367
       1 4975.17 5024.83
Encroach Node=6022.17
       1 4975.17 5024.83
Encroach Node=6002.147
       1  4974.9  5025.1
Encroach Node=5942
       1  4974.9  5025.1
Encroach Node=5882.069
       1 4975.17 5024.83
Encroach Node=5802.051
       1 4975.17 5024.83
Encroach Node=4787.943
       1 4974.24 5025.76
Encroach Node=3958.452
       1 4974.44 5025.56
Encroach Node=3194.88
       1 4974.44 5025.56
Encroach Node=3154.88
       1 4974.44 5025.56
Encroach Node=3095.88
       1 4974.44 5025.56
Encroach Node=3036.893
       1 4974.44 5025.56
Encroach Node=2996.893
       1 4974.44 5025.56
Encroach Node=2336.964
       1 4963.91 5018.27
Encroach Node=1402.847
       1 4973.75  5029.6
Encroach Node=886.787
       1 4973.75 5026.25
Encroach Node=802.62
       1 4971.97 5024.39
Encroach Node=743
       1 4971.97 5024.39
Encroach Node=684.818
       1 4971.97 5024.39
Encroach Node=560.82
       1 4973.75 5026.25
BEGIN DESCRIPTION:
FEMA Effective Floodway June 2007 + LOMR 16-06-0467P
END DESCRIPTION:
Computation Interval=1HOUR
Output Interval=1HOUR
Run HTab= 0
Run UNet= 0
Run PostProcess= 0
UNET Theta= 1
UNET ZTol= 0.02
UNET ZSATol= 0.1
UNET MxIter= 20
UNET MaxInSteps= 20
UNET DtIC= 0
UNET DtMin= 0
UNET MaxCRTS= 20
UNET WFStab= 2
UNET SFStab= 1
UNET WFX= 1
UNET SFX= 1
UNET Convert EG Bridges=-1
UNET Use Existing IB Tables=-1
Instantaneous Interval=1HOUR
Write IC File= 0
IC Time=0
Write Velocity= 0
Write Detailed= 0

--- G104-08-00.p01 (plan) ---

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Plan Title=FEMA Effective Multi-Profile 2016
Short Identifier=Eff+LOMR MP
Geom File=g01
Flow File=f01
Encroach Param=-1 ,0,0, 0
FEMA Effective Multi-Profile June 2007 + LOMR 16-06-0467P

--- G104-08-00.f02 (steady flow) ---

Flow Title=FEMA Effective Floodway 2016
Program Version=4.10
Number of Profiles= 2
Profile Names=1PCT_100yr,1PCTFloodway_100yr
River Rch & RM=G104-08-00,G104-08-00_0006 ,10418.47
       4       4
River Rch & RM=G104-08-00,G104-08-00_0006 ,9733.909
      48      48
River Rch & RM=G104-08-00,G104-08-00_0006 ,8538.89
     181     181
River Rch & RM=G104-08-00,G104-08-00_0006 ,7896.867
     183     183
River Rch & RM=G104-08-00,G104-08-00_0006 ,7876.866
     192     192
River Rch & RM=G104-08-00,G104-08-00_0006 ,7786.862
     201     201
River Rch & RM=G104-08-00,G104-08-00_0006 ,7706.817
     277     277
River Rch & RM=G104-08-00,G104-08-00_0006 ,7108.367
     495     495
River Rch & RM=G104-08-00,G104-08-00_0006 ,6022.17
     507     507
River Rch & RM=G104-08-00,G104-08-00_0006 ,5802.051
     566     566
River Rch & RM=G104-08-00,G104-08-00_0006 ,4787.943
     619     619
River Rch & RM=G104-08-00,G104-08-00_0006 ,3958.452
     738     738
River Rch & RM=G104-08-00,G104-08-00_0006 ,3194.88
  374.11  374.11
River Rch & RM=G104-08-00,G104-08-00_0006 ,2336.964
     452     452
River Rch & RM=G104-08-00,G104-08-00_0006 ,1402.847
     569     569
River Rch & RM=G104-08-00,G104-08-00_0006 ,886.787
     600     600
Boundary for River Rch & Prof#=G104-08-00,G104-08-00_0006 , 1
Up Type= 0
Dn Type= 3
Dn Slope=0.001
Boundary for River Rch & Prof#=G104-08-00,G104-08-00_0006 , 2
Up Type= 0
Dn Type= 3
Dn Slope=0.001
DSS Import GetInterval= 0
DSS Import GetPeak= 0
DSS Import FillOption= 0
Storage Area Elev=Detention 1     , 4
   18.13   17.93    17.8   17.44

--- G104-08-00.f01 (steady flow) ---

Flow Title=FEMA Effective Multi-Profile 2016
Program Version=4.10
Number of Profiles= 4
Profile Names=10PCT_10yr, 2PCT_50yr, 1PCT_100yr, 0.2PCT_500yr
River Rch & RM=G104-08-00,G104-08-00_0006 ,10418.47
       4       4       4       4
River Rch & RM=G104-08-00,G104-08-00_0006 ,9733.909
      33      43      48      61
River Rch & RM=G104-08-00,G104-08-00_0006 ,8538.89
     110     157     181     249
River Rch & RM=G104-08-00,G104-08-00_0006 ,7896.867
     111     158     183     251
River Rch & RM=G104-08-00,G104-08-00_0006 ,7876.866
     117     166     192     264
River Rch & RM=G104-08-00,G104-08-00_0006 ,7786.862
     122     173     201     275
River Rch & RM=G104-08-00,G104-08-00_0006 ,7706.817
     168     239     277     379
River Rch & RM=G104-08-00,G104-08-00_0006 ,7108.367
     300     428     495     679
River Rch & RM=G104-08-00,G104-08-00_0006 ,6022.17
     308     438     507     695
River Rch & RM=G104-08-00,G104-08-00_0006 ,5802.051
     343     489     566     776
River Rch & RM=G104-08-00,G104-08-00_0006 ,4787.943
     375     535     619     849
River Rch & RM=G104-08-00,G104-08-00_0006 ,3958.452
     447     638     738    1011
River Rch & RM=G104-08-00,G104-08-00_0006 ,3194.88
  163.32   305.9  374.11  671.51
River Rch & RM=G104-08-00,G104-08-00_0006 ,2336.964
     211     373     452     780
River Rch & RM=G104-08-00,G104-08-00_0006 ,1402.847
     265     470     569     926
River Rch & RM=G104-08-00,G104-08-00_0006 ,886.787
     284     497     600     968
Boundary for River Rch & Prof#=G104-08-00,G104-08-00_0006 , 1
Up Type= 0
Dn Type= 3
Dn Slope=0.001
Boundary for River Rch & Prof#=G104-08-00,G104-08-00_0006 , 2
Up Type= 0
Dn Type= 3
Dn Slope=0.001
Boundary for River Rch & Prof#=G104-08-00,G104-08-00_0006 , 3
Up Type= 0
Dn Type= 3
Dn Slope=0.001
Boundary for River Rch & Prof#=G104-08-00,G104-08-00_0006 , 4
Up Type= 0
Dn Type= 3
Dn Slope=0.001
DSS Import GetInterval= 0
DSS Import GetPeak= 0
DSS Import FillOption= 0
Storage Area Elev=Detention 1     , 4
   18.13   17.93    17.8   17.44

--- G104-08-00.g01 (geometry) ---

Geom Title=G104-08-00
Program Version=4.10

River Reach=G104-08-00      ,G104-08-00_0006
Reach XY= 30
 3202920.300048113819946.2700543 3202923.610080913819965.3100424
 3202940.170087113819985.1800814 3202949.509963413819990.1498878
 3204697.939865513820083.7199106 3204717.110102813820091.6099867
 3204734.019845913820107.3901388 3204744.1599174 13820125.430129
  3204748.67007913820152.4799437 3204718.229851213820783.7700197
 3204715.749869313820895.0001122   3204595.06015 13822732.480033
 3204539.999892713824136.9998618 3204525.999920713824171.0001218
 3204500.749971213824192.0000799 3204467.000038713824200.0000639
 3202839.750012413824114.9999058 3202806.250079413824114.9999058
 3202777.500136913824126.9998818 3202755.499852813824144.9998458
 3202742.499878813824174.0001159 3202684.249995313825300.0001604
 3202673.750016313825331.0000984 3202646.750070313825357.0000464
 3202613.000137813825367.0000264  3202031.74998813825340.0000804
 3201977.000097413825357.0000464 3201723.999947313825635.0001466
 3201513.500040213825834.0000767 3201432.999873113825951.9998407

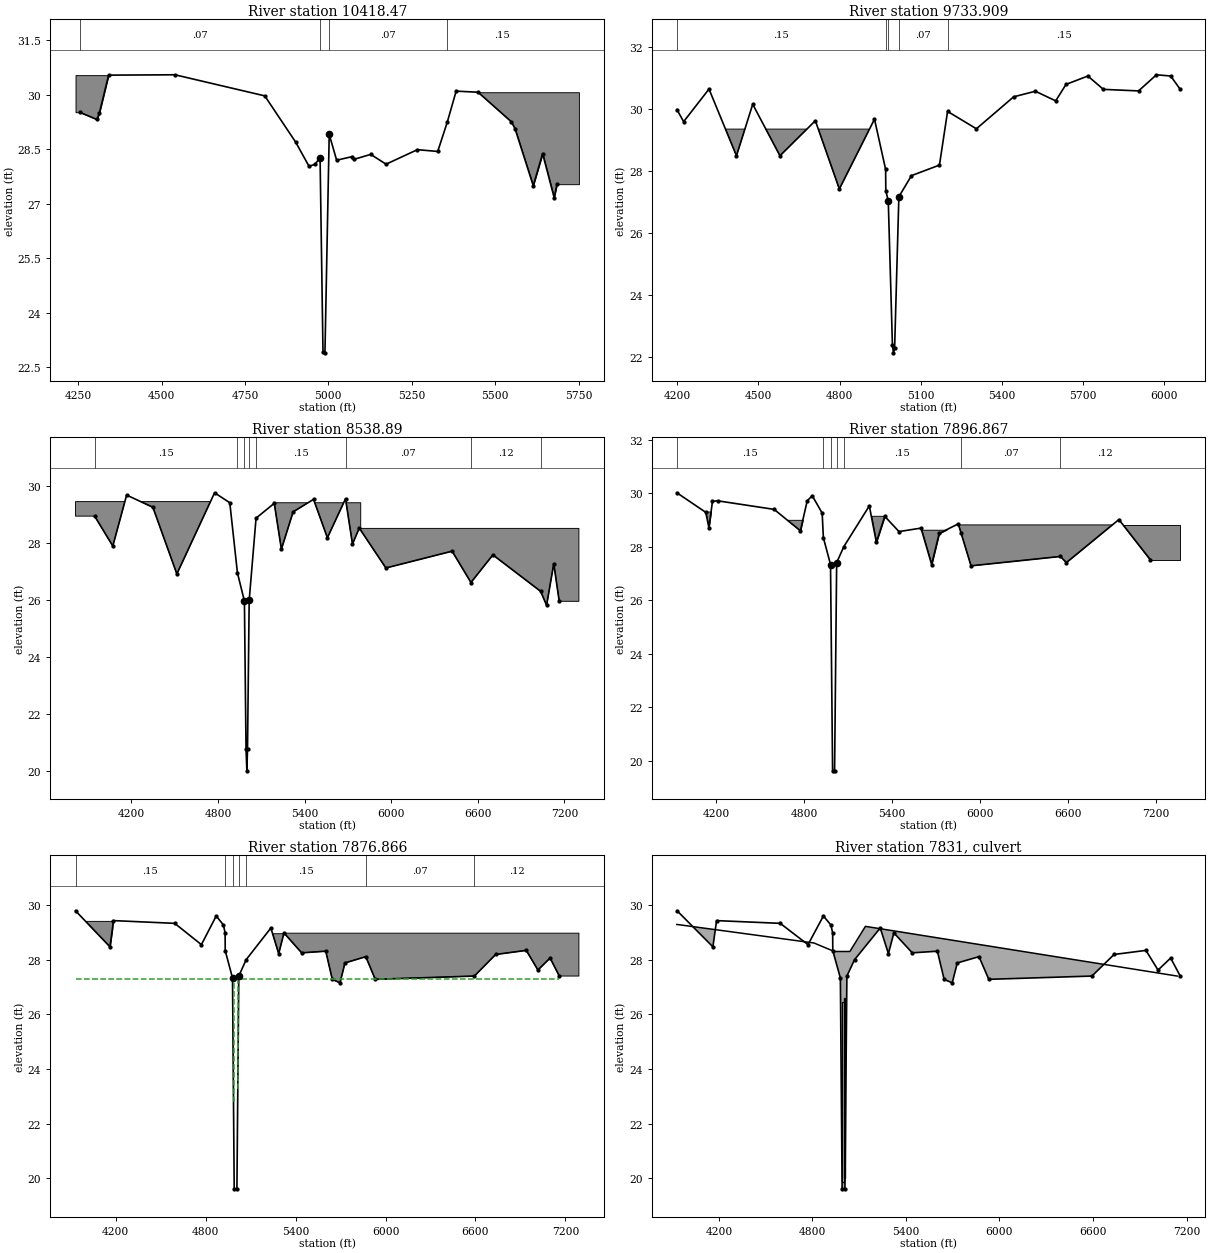
Type RM Length L Ch R = 1 ,10418.47,1124.08,684.56,338.79
XS GIS Cut Line= 6
     3202185.355    13819943.886     3202739.836    13819955.992
     3202899.197    13819956.483     3202936.883    13819956.483
     3203024.392    13819955.844     3203512.253    13819621.837
#Sta/Elev= 29
 4254.75   29.52 4306.59   29.32 4313.88    29.5 4341.44   30.54 4540.26   30.55
 4809.36   29.97 4901.84    28.7 4942.28   28.03 4960.19   28.09 4975.16   28.27
 4983.92   22.93 4989.79    22.9 5002.59   28.91 5024.84    28.2 5072.36    28.3
 5075.53   28.22 5127.02   28.36 5172.98   28.09 5266.98   28.49 5327.74   28.44
 5356.17   29.24 5382.98    30.1 5448.76   30.07 5548.09   29.26 5559.31   29.07
    5614    27.5 5642.13   28.38 5676.75   27.17 5685.17   27.54
#Mann= 4 ,-1 , 0
 4254.75     .07       0 4975.16    .015       0 5002.59     .07       0
 5356.17     .15       0
#Block Obstruct= 2 ,-1
 4242.31 4341.08   30.54 5448.36 5750.87   30.07
Bank Sta=4975.16,5002.59
XS Rating Curve= 0 ,0
Exp/Cntr=0.3,0.1

Type RM Length L Ch R = 1 ,9733.909,278.36,1195.02,1694.87
XS GIS Cut Line= 6
     3203541.001    13820816.598      3203553.02    13820672.366
     3203585.731    13820045.411      3203586.56    13820036.269
     3203590.535    13819950.536     3203650.583    13818957.166
#Sta/Elev= 30
  4198.1   29.98 4223.18   29.59 4317.02   30.64  4418.7   28.49 4478.78   30.15
 4579.62   28.49 4710.54   29.62  4799.4   27.42  4929.4   29.67 4970.64   28.05
 4971.23   27.37 4980.41   27.03 4995.76   22.39 4999.57   22.14 5003.83   22.28
 5019.59   27.17 5066.23   27.85 5169.78   28.19 5199.82   29.92 5306.46   29.36
  5444.4   30.39 5524.66   30.57 5599.92   30.26 5638.16   30.79 5718.94   31.06
 5776.46   30.63  5906.5   30.58 5972.78    31.1 6025.48   31.06 6060.82   30.63
#Mann= 5 ,-1 , 0
  4198.1     .15       0 4970.64     .07       0 4980.41    .015       0
 5019.59     .07       0 5199.82     .15       0
#Block Obstruct= 1 ,-1
 4238.91 4907.28   29.35
Bank Sta=4980.41,5019.59
XS Rating Curve= 0 ,0
Exp/Cntr=0.3,0.1

Type RM Length L Ch R = 1 ,8538.89 ,401.33,642.02,659.96
XS GIS Cut Line= 6
     3203726.743    13820399.271      3204690.11    13820143.483
     3204714.291    13820143.372     3204730.266    13820142.933
     3204763.292    13820143.558     3206909.987    13820191.939
#Sta/Elev= 30
 3946.38   28.93 4072.28   27.88 4167.96   29.67 4349.76   29.24 4515.72    26.9
  4776.9   29.75 4882.32    29.4 4935.12   26.94 4983.48   25.95  4994.7   20.76
 5000.51   19.99 5004.88   20.74 5016.52   25.97  5064.1   28.86 5190.26   29.38
  5239.6   27.77 5320.86   29.08 5462.32   29.52 5558.18   28.17 5683.66   29.54
 5731.84   27.95 5778.92   28.51 5963.12   27.11 6421.92    27.7  6552.3    26.6
 6704.08   27.57 7034.86   26.29 7076.08    25.8 7125.74   27.26 7163.56   25.94
#Mann= 8 ,-1 , 0
 3946.38     .15       0 4935.12     .07       0 4983.48    .015       0
 5016.52     .07       0  5064.1     .15       0 5683.66     .07       0
  6552.3     .12       0 7034.86     .07       0
#Block Obstruct= 3 ,-1
 3813.99 4774.18   29.44 5188.28 5788.96    29.4 5775.31 7299.77    28.5
Bank Sta=4983.48,5016.52
XS Rating Curve= 0 ,0
Exp/Cntr=0.3,0.1

Type RM Length L Ch R = 1 ,7896.867,20,20,20.09
XS GIS Cut Line= 6
      3203654.09    13820726.858     3204582.419    13820780.715
     3204730.826    13820784.809     3204811.719    13820788.179
      3206271.18     13820875.21     3206877.376    13820904.926
#Sta/Elev= 30
 3931.44   30.01  4128.2   29.28  4149.9   28.71 4174.26   29.69 4209.18   29.71
 4594.56   29.39  4773.6   28.59  4820.1   29.71 4854.46    29.9 4922.18   29.25
  4930.4   28.33 4979.07   27.33 4993.14   19.63 5006.79   19.62 5020.93    27.4
 5070.12      28 5243.64   29.52 5291.58   28.16 5348.88   29.13 5445.94   28.56
 5595.98   28.69 5668.46   27.33 5719.96   28.49 5850.26   28.85 5868.42   28.52
 5937.06   27.28 6546.36   27.63 6587.38    27.4 6945.22   29.01 7159.72   27.51
#Mann= 7 ,-1 , 0
 3931.44     .15       0  4930.4     .07       0 4979.07    .015       0
 5020.93     .07       0 5070.12     .15       0 5868.42     .07       0
 6546.36     .12       0
#Block Obstruct= 5 ,-1
 4032.42  4209.9   29.31 4537.54 4824.23      29 5220.14 5356.66   29.15
 5593.29 5811.72   28.63 5843.57 7363.48   28.81
Bank Sta=4979.07,5020.93
XS Rating Curve= 0 ,0
Exp/Cntr=0.5,0.3

Type RM Length L Ch R = 1 ,7876.866,90.01,90,90.39
XS GIS Cut Line= 6
     3203652.932    13820746.825     3204581.581      13820800.7
     3204730.092    13820804.796     3204810.707    13820808.154
     3206270.095    13820895.181     3206876.397    13820924.902
#Sta/Elev= 30
 3931.38   29.79 4161.18   28.47 4184.78   29.43 4593.18   29.33  4771.4   28.55
 4870.28    29.6 4918.32   29.27 4929.62   28.98  4930.4   28.33 4979.07   27.33
 4990.32   19.61 5008.44   19.61 5020.93    27.4 5070.12      28    5235   29.16
 5287.36   28.22 5322.38   28.98 5440.48   28.25 5601.44   28.31 5644.86   27.28
 5696.68   27.15 5729.28   27.88 5868.46   28.11  5931.6   27.28 6593.16    27.4
 6735.06   28.19 6939.54   28.34 7017.26   27.62 7098.38   28.06 7159.84    27.4
#Mann= 7 ,-1 , 0
 3931.38     .15       0  4930.4     .07       0 4979.07    .015       0
 5020.93     .07       0 5070.12     .15       0 5868.46     .07       0
 6593.16     .12       0
#XS Ineff= 2 , 0
       0  4985.7    27.3  5014.3       0    27.3
Permanent Ineff=
       F       F
#Block Obstruct= 3 ,-1
 3909.56 4178.04   29.42 5211.04 5329.35   28.95 5320.25 7290.67   28.97
Bank Sta=4979.07,5020.93
XS Rating Curve= 0 ,0
Exp/Cntr=0.5,0.3

Type RM Length L Ch R = 2 ,7831    ,,,
BEGIN DESCRIPTION:
2 Box Culverts @ Avenue X
END DESCRIPTION:
Bridge Culvert--1,0,-1,-1, 0
Deck Dist Width WeirC Skew NumUp NumDn MinLoCord MaxHiCord MaxSubmerge Is_Ogee
6,81,2.6,0, 6, 6, , , 0.95, 0, 0,0,,
    3930    4810    4940    5040    5140    7140
   29.29   28.61    28.3    28.3   29.22    27.4
       0       0       0       0       0       0
    3930    4810    4940    5040    5140    7140
   29.29   28.61    28.3    28.3   29.22    27.4
       0       0       0       0       0       0
Culvert=2,6.6,8,81,0.012,0.5,1,8,2,19.86,4995.7,19.65,4995.7,Culvert #2  , 0 ,6
Culvert Bottom n=0.012
Culvert=2,6.6,8,81,0.012,0.5,1,8,2,20,5004.3,19.64,5004.3,Culvert #1  , 0 ,6
Culvert Bottom n=0.012
BC Design=,, 0 ,, 0 ,,,,,,
BC HTab HWMax=29.79
BC Use User HTab Curves=0
BC User HTab FreeFlow(D)= 0

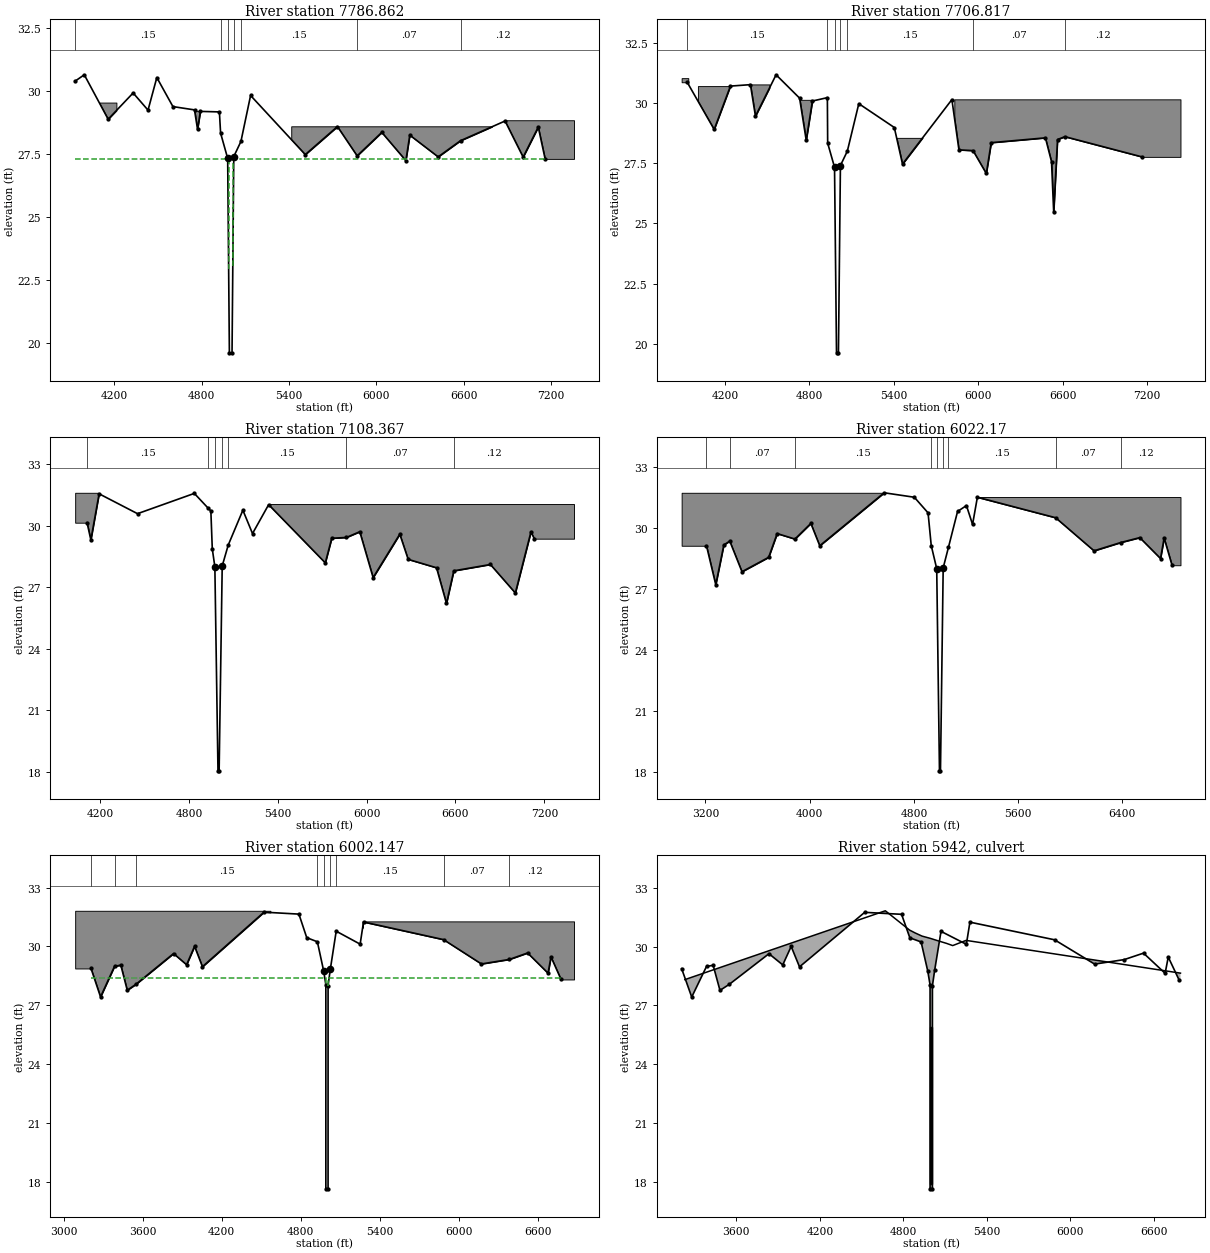
Type RM Length L Ch R = 1 ,7786.862,80.03,80.04,80.3
XS GIS Cut Line= 6
      3203647.72    13820836.674     3204577.809    13820890.632
     3204726.788    13820894.736     3204806.155    13820898.043
     3206265.213     13820985.05     3206871.991    13821014.794
#Sta/Elev= 30
  3931.1   30.39 3993.74   30.64 4157.74   28.88 4329.38   29.92 4431.72   29.24
 4492.22   30.53 4602.84   29.38  4751.1   29.25 4771.98   28.48  4791.5   29.19
 4922.16   29.17  4930.4   28.33 4979.07   27.33 4990.77   19.63 5009.01   19.63
 5020.93    27.4 5070.12      28 5136.48   29.82  5512.3   27.48  5733.4   28.59
 5868.68   27.43 6038.16   28.36 6203.56   27.24 6230.46   28.25 6425.38   27.39
 6579.12   28.03 6885.16   28.81 7009.44   27.38  7113.4   28.57 7160.38   27.31
#Mann= 7 ,-1 , 0
  3931.1     .15       0  4930.4     .07       0 4979.07    .015       0
 5020.93     .07       0 5070.12     .15       0 5868.68     .07       0
 6579.12     .12       0
#XS Ineff= 2 , 0
       0  4985.7    27.3  5014.3       0    27.3
Permanent Ineff=
       F       F
#Block Obstruct= 4 ,-1
 3986.92 4214.45   29.54 4728.67 4792.38   29.21 5415.81 6794.65    28.6
 6881.11 7358.93   28.84
Bank Sta=4979.07,5020.93
XS Rating Curve= 0 ,0
Exp/Cntr=0.5,0.3

Type RM Length L Ch R = 1 ,7706.817,623.96,598.45,583.18
XS GIS Cut Line= 6
     3203643.086     13820916.54     3204574.457    13820970.572
     3204723.851    13820974.683     3204802.108    13820977.944
     3206260.873    13821064.933     3206868.074    13821094.698
#Sta/Elev= 30
 3932.48   30.86 4124.24    28.9 4239.62    30.7 4381.72   30.76  4417.4   29.45
 4563.94   31.17 4730.86    30.2    4778   28.45 4822.02   30.08 4928.18   30.22
  4930.4   28.33 4979.07   27.33 4993.14   19.63 5006.79   19.62 5020.93    27.4
 5070.12      28 5151.52   29.97 5403.66   28.98 5461.92   27.46  5812.8   30.14
 5862.78   28.05 5962.94   28.02 6057.24   27.07 6091.98   28.35    6477   28.55
 6520.38   27.56 6535.84   25.46 6563.06   28.48 6615.08    28.6 7162.48   27.76
#Mann= 7 ,-1 , 0
 3932.48     .15       0 4928.18     .07       0 4979.07    .015       0
 5020.93     .07       0 5070.12     .15       0 5962.94     .07       0
 6615.08     .12       0
#Block Obstruct= 6 ,-1
 3893.09 3940.28   31.03 4008.77 4237.08    30.7 4381.67 4517.13   30.77
 4721.09  4832.2   30.13 5329.35  5675.2   28.55 5829.92 7436.29   30.15
Bank Sta=4979.07,5020.93
XS Rating Curve= 0 ,0
Exp/Cntr=0.3,0.1

Type RM Length L Ch R = 1 ,7108.367,1069.53,1086.2,1092.03
XS GIS Cut Line= 6
     3203786.496    13821551.873     3204583.611    13821575.757
     3204668.571    13821571.416     3204718.235    13821571.543
     3204867.229    13821572.771     3206804.787    13821647.408
#Sta/Elev= 30
 4112.06   30.15 4137.76   29.31 4193.47   31.56 4452.94   30.59 4836.53   31.58
 4928.46   30.87 4948.16   30.72  4957.8   28.87 4975.17      28 4996.24   18.04
 5003.99   18.04 5024.83   28.04 5065.54   29.06 5164.36   30.76  5229.4   29.62
 5338.33   31.03 5720.91   28.19 5764.44   29.39 5863.78   29.43 5953.79   29.71
 6043.86   27.47 6223.99   29.59 6280.67   28.36 6472.04   27.95 6539.22   26.21
 6588.63    27.8 6835.92   28.11  7004.3   26.72 7109.61    29.7 7132.26   29.37
#Mann= 7 ,-1 , 0
 4112.06     .15       0 4928.46     .07       0 4975.17    .015       0
 5024.83     .07       0 5065.54     .15       0 5863.78     .07       0
 6588.63     .12       0
#Block Obstruct= 2 ,-1
 4031.85 4191.13   31.61 5337.88 7400.46   31.06
Bank Sta=4975.17,5024.83
XS Rating Curve= 0 ,0
Exp/Cntr=0.3,0.1

Type RM Length L Ch R = 1 ,6022.17 ,20.24,20.02,20.07
XS GIS Cut Line= 6
     3202826.081    13822549.029     3204520.472    13822647.697
     3204588.368    13822655.071     3204675.093    13822656.804
      3204871.42    13822662.309     3206392.806     13822731.47
#Sta/Elev= 30
 3208.81   29.13 3280.04   27.21 3341.93   29.17 3387.39   29.36 3481.13   27.85
 3685.79   28.56 3751.04   29.73 3887.43   29.46 4009.53   30.23  4077.7   29.13
 4572.22   31.74 4803.34   31.52  4908.8   30.75 4933.13   29.14 4975.17      28
 4996.24   18.04 5003.99   18.04 5024.83   28.04 5065.54   29.06 5135.09   30.82
 5203.26   31.11  5250.2   30.18 5287.13   31.52 5887.56   30.51 6182.15   28.88
 6387.59   29.29 6533.14   29.53 6692.24    28.5 6719.81   29.51 6780.47   28.17
#Mann= 9 ,-1 , 0
 3208.81     .15       0 3387.39     .07       0 3887.43     .15       0
 4933.13     .07       0 4975.17    .015       0 5024.83     .07       0
 5065.54     .15       0 5887.56     .07       0 6387.59     .12       0
#Block Obstruct= 2 ,-1
  3018.2 4569.97   31.74 5288.96 6845.28   31.53
Bank Sta=4975.17,5024.83
XS Rating Curve= 0 ,0
Exp/Cntr=0.5,0.3

Type RM Length L Ch R = 1 ,6002.147,121.42,120.08,120.41
XS GIS Cut Line= 6
     3202824.919    13822568.995      3204518.81    13822667.634
     3204587.105    13822675.051     3204674.588    13822676.798
     3204870.686    13822682.296     3206391.897    13822751.449
#Sta/Elev= 30
  3206.9   28.88 3279.28   27.43  3385.5   28.99 3433.26   29.05 3482.22   27.77
  3549.5   28.08 3834.08   29.64 3933.16   29.07  3993.7   30.01 4053.56   28.97
 4521.76   31.75 4786.64   31.65 4846.21   30.45 4926.98   30.24  4974.9   28.75
 4991.35   28.05  4991.4   17.65  5008.2   17.65 5008.31   28.01  5025.1   28.83
 5070.01   30.78 5251.98   30.12 5277.56   31.25 5885.84   30.35 6173.52   29.11
  6385.9   29.34 6524.52   29.67 6679.78   28.64  6702.2   29.47  6778.8   28.32
#Mann= 9 ,-1 , 0
  3206.9     .15       0  3385.5     .07       0  3549.5     .15       0
 4926.98     .07       0  4974.9    .015       0  5025.1     .07       0
 5070.01     .15       0 5885.84     .07       0  6385.9     .12       0
#XS Ineff= 2 , 0
       0 4991.35    28.4 5008.31       0    28.4
Permanent Ineff=
       F       F
#Block Obstruct= 2 ,-1
 3086.46 4569.97   31.82 5270.76 6877.13   31.28
Bank Sta=4974.9,5025.1
XS Rating Curve= 0 ,0
Exp/Cntr=0.5,0.3

Type RM Length L Ch R = 2 ,5942    ,,,
BEGIN DESCRIPTION:
2 Box Culverts @ 13th Street
END DESCRIPTION:
Bridge Culvert--1,0,-1,-1, 0
Deck Dist Width WeirC Skew NumUp NumDn MinLoCord MaxHiCord MaxSubmerge Is_Ogee
3,100,2.6,0, 11, 11, , , 0.95, 0, 0,0,,
    3230    4670    4844    4884    4934    4994    5059    5109    5154    5250
    6790
   28.32   31.83  30.846    30.7  30.538  30.422  30.276  30.169  30.055   30.32
   28.65
       0       0       0       0       0       0       0       0       0       0
       0
    3230    4670    4844    4884    4934    4994    5059    5109    5154    5250
    6790
   28.32   31.83  30.846    30.7  30.538  30.422  30.276  30.169  30.055   30.32
   28.65
       0       0       0       0       0       0       0       0       0       0
       0
Culvert=2,8,8,100,0.012,0.7,1,8,3,17.89,4995.5,17.67,4995.5,Culvert #1  , 0 ,3
Culvert Bottom n=0.012
Culvert=2,8,8,100,0.012,0.7,1,8,3,17.88,5004,17.64,5004,Culvert #2  , 0 ,3
Culvert Bottom n=0.012
BC Design=,, 0 ,, 0 ,,,,,,
BC HTab HWMax=31.79
BC Use User HTab Curves=0
BC User HTab FreeFlow(D)= 0

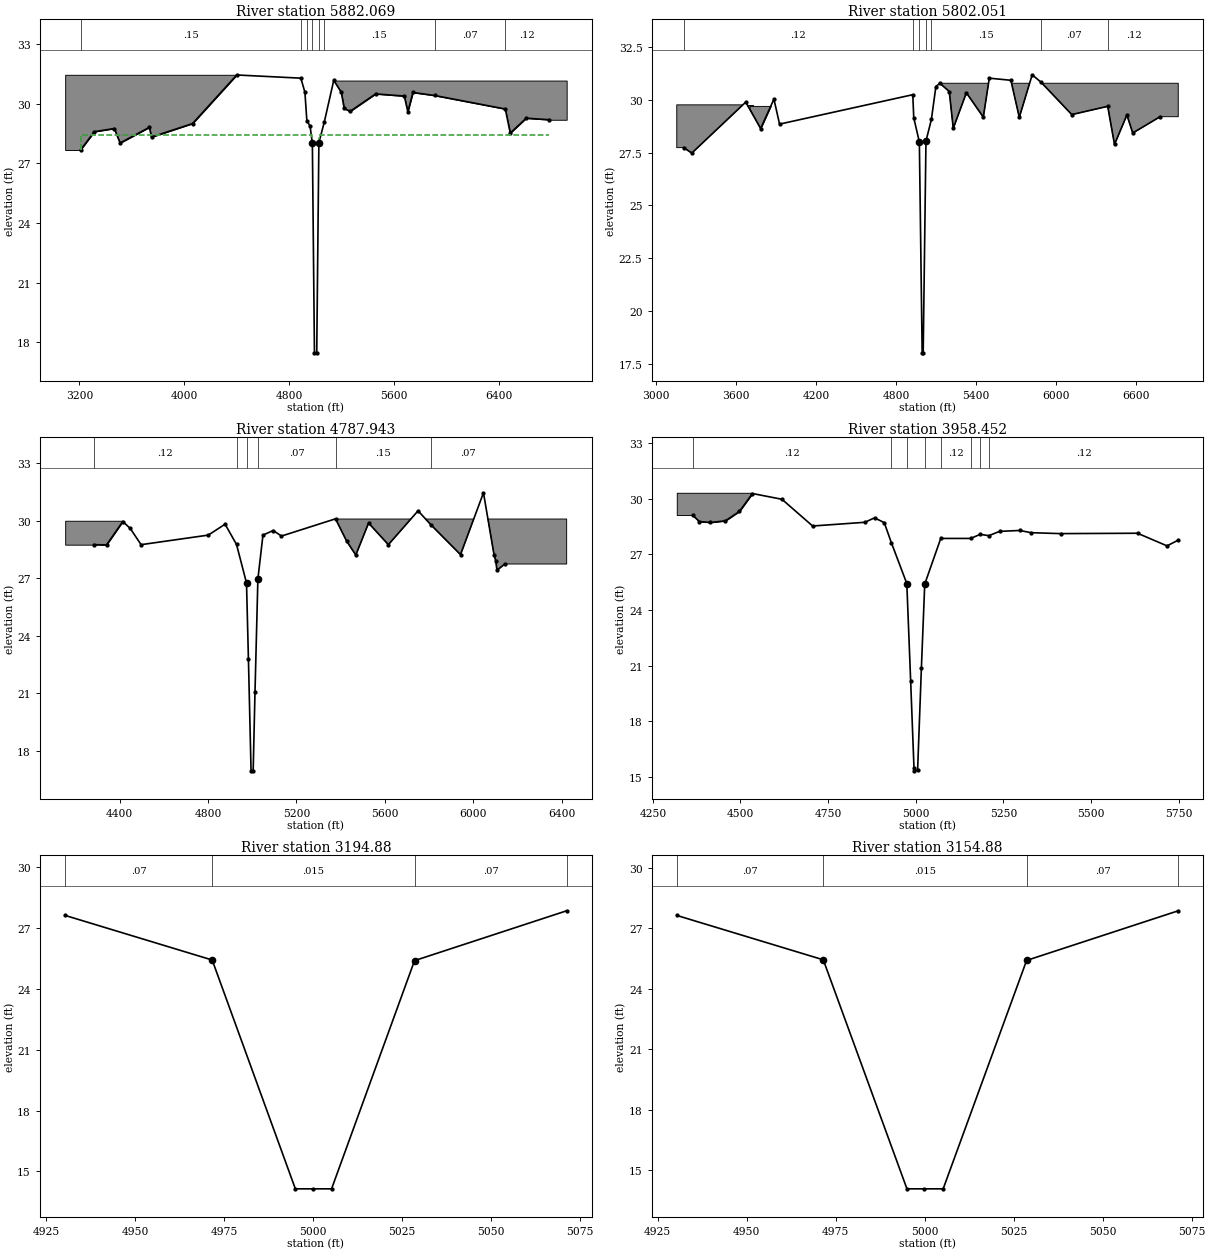
Type RM Length L Ch R = 1 ,5882.069,81.47,80.02,80.28
XS GIS Cut Line= 6
     3202817.943    13822688.792     3204508.838    13822787.257
     3204579.522    13822794.933     3204671.563     13822796.76
     3204866.279     13822802.22     3206386.448    13822871.326
#Sta/Elev= 30
 3207.92   27.67 3313.34   28.59 3465.36   28.75  3509.6   28.02 3732.66   28.81
 3749.12   28.32  4062.1      29 4398.88   31.44 4887.44   31.28 4918.42   30.57
 4933.13   29.14  4957.8   28.87 4975.17      28 4991.01   17.48 5008.45   17.48
 5024.83   28.04 5065.54   29.06 5138.12   31.17  5195.5   30.57  5217.6   29.76
 5262.48   29.61 5457.36   30.49 5675.96   30.38  5702.8   29.59 5741.68   30.56
 5906.16   30.41 6445.88   29.73 6483.38   28.52 6605.18   29.27 6781.36   29.19
#Mann= 8 ,-1 , 0
 3207.92     .15       0 4887.44     .12       0 4933.13     .07       0
 4975.17    .015       0 5024.83     .07       0 5065.54     .15       0
 5906.16     .07       0 6445.88     .12       0
#XS Ineff= 2 , 0
       0 4975.17    28.4 5024.83       0    28.4
Permanent Ineff=
       F       F
#Block Obstruct= 2 ,-1
 3091.01 4387.94   31.45 5138.79 6913.54   31.16
Bank Sta=4975.17,5024.83
XS Rating Curve= 0 ,0
Exp/Cntr=0.5,0.3

Type RM Length L Ch R = 1 ,5802.051,857.91,1014.11,1014.11
XS GIS Cut Line= 6
     3202813.292    13822768.657      3204502.19    13822867.005
     3204574.468    13822874.855     3204669.545    13822876.735
     3204863.341    13822882.169     3206382.815    13822951.243
#Sta/Elev= 30
  3207.4   27.73  3267.3   27.47 3672.48   29.88 3783.96   28.63 3883.83   30.02
 3926.13   28.84 4925.98   30.23 4933.13   29.14 4975.17      28 4996.24   18.04
 5003.99   18.04 5024.83   28.04 5065.54   29.06 5099.15   30.61 5129.29   30.77
 5199.65   30.38 5229.66   28.64 5327.99   30.32 5455.12   29.17 5500.16   31.01
 5662.16   30.91 5725.15   29.16 5821.89   31.17 5888.25   30.82  6119.2   29.29
 6388.68   29.68 6439.72   27.88 6532.66   29.27 6576.67   28.42 6781.87   29.19
#Mann= 7 ,-1 , 0
  3207.4     .12       0 4925.98     .07       0 4975.17    .015       0
 5024.83     .07       0 5065.54     .15       0 5888.25     .07       0
 6388.68     .12       0
#Block Obstruct= 3 ,-1
 3154.72  3728.1   29.75  3700.8 3873.72    29.7 5125.14 6918.09   30.77
Bank Sta=4975.17,5024.83
XS Rating Curve= 0 ,0
Exp/Cntr=0.3,0.1

Type RM Length L Ch R = 1 ,4787.943,149.42,829.49,1368.97
XS GIS Cut Line= 6
     3203880.181    13823635.417     3204478.857    13823874.204
     3204522.508    13823886.091     3204642.788    13823890.307
     3204680.443    13823894.095     3205690.838    13823915.577
#Sta/Elev= 30
 4284.36   28.75 4340.96   28.74 4414.22   29.96  4447.9    29.6 4497.12   28.75
 4801.38   29.25 4877.33   29.82 4929.05   28.76 4974.24   26.75 4982.94   22.77
 4994.85   16.94 5004.37   16.94 5012.63   21.05 5025.76   26.96 5048.66   29.25
 5094.99   29.49 5132.58    29.2 5377.04    30.1  5427.6   28.93 5469.02   28.21
 5526.68   29.88 5616.28   28.75 5750.66   30.52 5808.58   29.79 5942.82   28.23
 6046.66   31.46 6094.54   28.22  6102.7   27.89 6107.68   27.41 6143.16   27.74
#Mann= 6 ,-1 , 0
 4284.36     .12       0 4929.05     .07       0 4974.24    .015       0
 5025.76     .07       0 5377.04     .15       0 5808.58     .07       0
#Block Obstruct= 2 ,-1
 4153.58 4415.24      30 5379.41 6423.21   30.09
Bank Sta=4974.24,5025.76
XS Rating Curve= 0 ,0
Exp/Cntr=0.3,0.1

Type RM Length L Ch R = 1 ,3958.452,763.57,763.57,763.57
XS GIS Cut Line= 6
     3203778.867    13823587.427     3203998.889    13824111.228
     3203992.254    13824153.021     3203986.848    13824334.971
       3203971.2    13824498.887     3203944.506    13824925.985
#Sta/Elev= 30
 4363.52   29.12  4382.5   28.77 4414.38   28.72 4457.22   28.81 4497.18   29.32
 4534.22   30.28 4618.32   29.97 4705.84   28.53  4854.8   28.73  4882.4   28.97
 4910.14   28.71  4930.4   27.63 4974.44   25.43 4985.42   20.18 4994.89   15.51
 4995.05   15.34 5005.22   15.37 5016.07   20.89 5025.56    25.4 5071.25   27.86
 5156.53   27.86 5183.78   28.08 5208.46   28.01 5238.96   28.24    5297   28.29
 5328.62   28.17 5412.94   28.12 5632.46   28.14 5716.62   27.46 5748.68   27.77
#Mann= 8 ,-1 , 0
 4363.52     .12       0  4930.4     .07       0 4974.44    .015       0
 5025.56     .07       0 5071.25     .12       0 5156.53     .07       0
 5183.78     .15       0 5208.46     .12       0
#Block Obstruct= 1 ,-1
 4318.32 4533.11   30.32
Bank Sta=4974.44,5025.56
XS Rating Curve= 0 ,0
Exp/Cntr=0.3,0.1

Type RM Length L Ch R = 1 ,3194.88 ,40,40,40
BEGIN DESCRIPTION:
Added Cross Section by coping XS 3958.452 and adjusting flowline elevation.
END DESCRIPTION:
XS GIS Cut Line= 2
 3203232.410644413824070.2244048 3203224.343075213824210.0630358
#Sta/Elev= 7
  4930.4   27.63 4971.69   25.43 4995.05   14.14 4999.91   14.14 5005.22   14.14
 5028.52    25.4 5071.25   27.86
#Mann= 4 ,-1 , 0
  4930.4     .07       0 4971.69    .015       0 5028.52     .07       0
 5071.25    .012       0
Bank Sta=4971.69,5028.52
XS Rating Curve= 0 ,0
Exp/Cntr=0.3,0.1

Type RM Length L Ch R = 1 ,3154.88 ,118.08,117.99,117.88
BEGIN DESCRIPTION:
Added Cross Section by coping XS 3958.452 and adjusting flowline elevation.
END DESCRIPTION:
XS GIS Cut Line= 2
 3203192.476997213824067.9206036  3203184.40942813824207.7592347
#Sta/Elev= 7
  4930.4   27.63 4971.55   25.43 4995.05   14.08 4999.91   14.08 5005.22   14.08
 5028.66    25.4 5071.25   27.86
#Mann= 4 ,-1 , 0
  4930.4     .07       0 4971.55    .015       0 5028.66     .07       0
 5071.25    .012       0
Bank Sta=4971.55,5028.66
XS Rating Curve= 0 ,0
Exp/Cntr=0.3,0.1

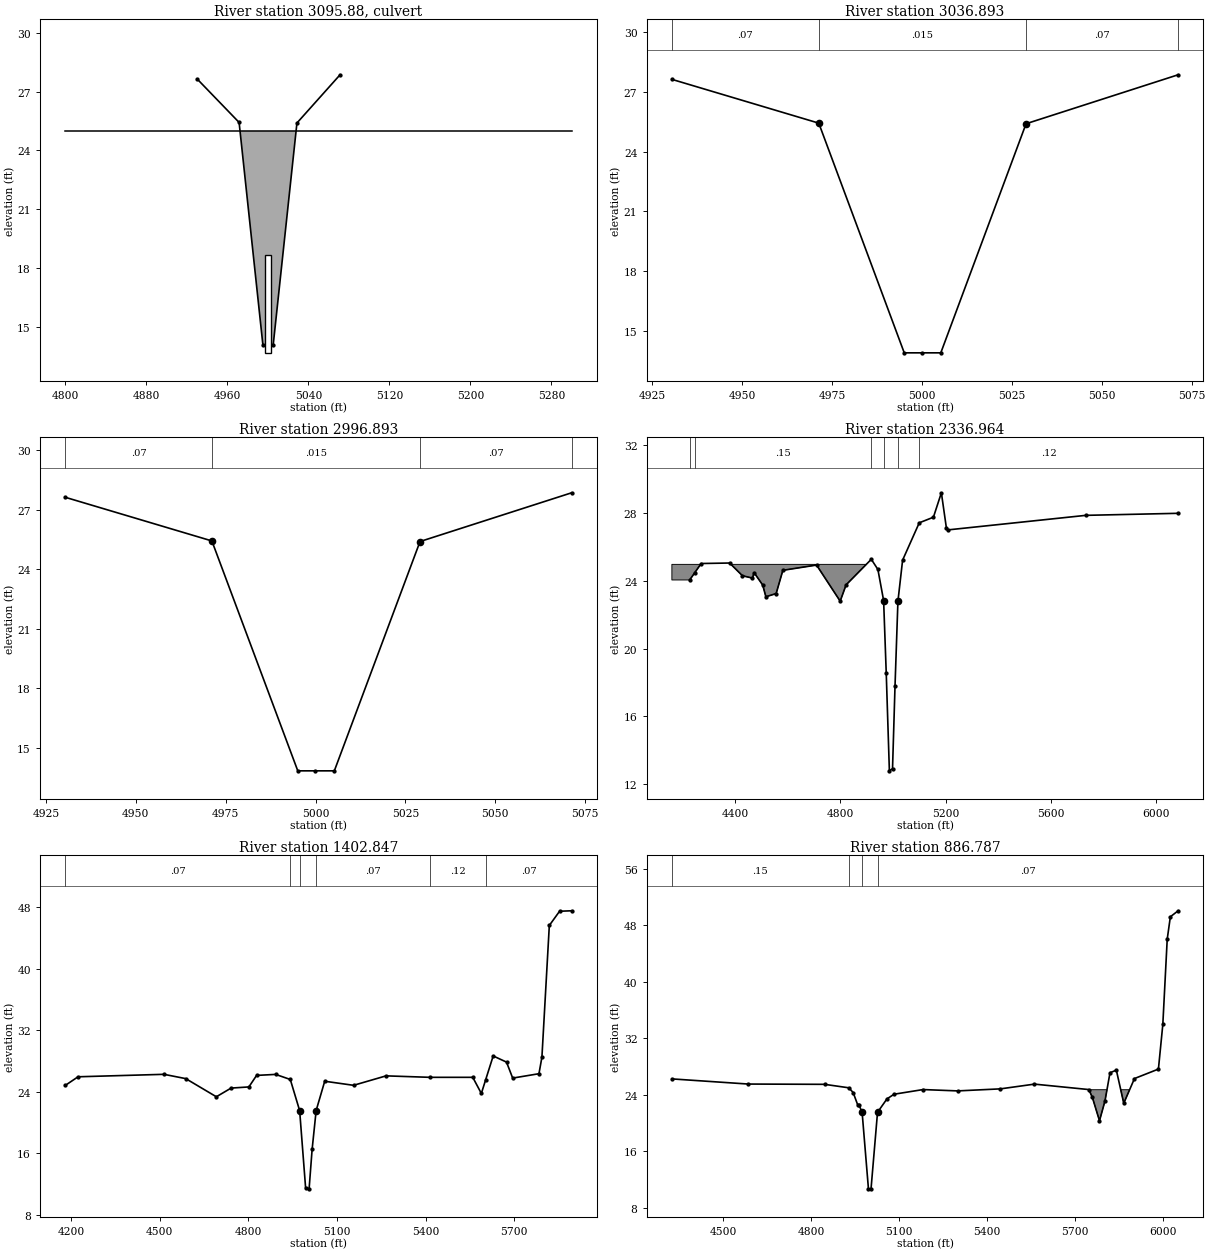
Type RM Length L Ch R = 2 ,3095.88 ,,,
Bridge Culvert--1,0,-1,-1, 0
Deck Dist Width WeirC Skew NumUp NumDn MinLoCord MaxHiCord MaxSubmerge Is_Ogee
54,10,2.6,0, 2, 2, 25, , 0.95, 0, 4,4,,
    4800    5300
      25      25
                
    4800    5300
      25      25
                
Culvert=2,5,6,100,0.012,0.5,1,8,2,13.68,5000,13.54,5000,Culvert #1  , 0 ,9
Culvert Bottom n=0.012
BC Design=,, 0 ,, 0 ,,,,,,
BC HTab HWMax=27.86
BC Use User HTab Curves=0
BC User HTab FreeFlow(D)= 0

Type RM Length L Ch R = 1 ,3036.893,40,40,40
BEGIN DESCRIPTION:
Added Cross Section by coping XS 3958.452 and adjusting flowline elevation.
END DESCRIPTION:
XS GIS Cut Line= 2
  3203074.401774 13824061.721469 3203066.870949213824201.5814255
#Sta/Elev= 7
  4930.4   27.63 4971.27   25.43 4995.05   13.89 4999.91   13.89 5005.22   13.89
 5028.94    25.4 5071.25   27.86
#Mann= 4 ,-1 , 0
  4930.4     .07       0 4971.27    .015       0 5028.94     .07       0
 5071.25    .012       0
Bank Sta=4971.27,5028.94
XS Rating Curve= 0 ,0
Exp/Cntr=0.3,0.1

Type RM Length L Ch R = 1 ,2996.893,724,659.92,623
BEGIN DESCRIPTION:
Added Cross Section by coping XS 3958.452 and adjusting flowline elevation.
END DESCRIPTION:
XS GIS Cut Line= 2
 3203034.459596713824059.5705547 3203026.928771913824199.4305112
#Sta/Elev= 7
  4930.4   27.63 4971.15   25.43 4995.05   13.83 4999.91   13.83 5005.22   13.83
 5029.06    25.4 5071.25   27.86
#Mann= 4 ,-1 , 0
  4930.4     .07       0 4971.15    .015       0 5029.06     .07       0
 5071.25    .012       0
Bank Sta=4971.15,5029.06
XS Rating Curve= 0 ,0
Exp/Cntr=0.3,0.1

Type RM Length L Ch R = 1 ,2336.964,263.93,934.12,1462.26
XS GIS Cut Line= 6
     3201950.551    13824487.318     3202436.075    13824511.768
      3202759.33    13824519.452     3202930.621     13824521.94
     3203155.887    13824516.662     3203805.908    13824525.541
#Sta/Elev= 30
 4226.86   24.04 4245.42   24.45 4270.42   25.01 4378.68   25.04  4427.4   24.29
 4465.62   24.15 4471.84   24.47 4504.46   23.74  4516.5   23.05 4555.52   23.24
  4581.1   24.61 4709.08   24.92 4798.88   22.79 4821.25   23.75  4917.1   25.26
 4942.18   24.66 4963.91   22.83  4973.9   18.54 4985.81   12.79 4997.79   12.92
 5007.25   17.79 5018.27   22.78 5036.09   25.21 5099.35   27.41 5153.18   27.74
 5183.41   29.18 5202.72   27.08 5206.84   26.99  5732.6   27.85 6083.14   27.97
#Mann= 6 ,-1 , 0
 4226.86     .07       0 4245.42     .15       0  4917.1     .07       0
 4963.91    .015       0 5018.27     .07       0 5099.35     .12       0
#Block Obstruct= 1 ,-1
 4159.27 4907.28   24.96
Bank Sta=4963.91,5018.27
XS Rating Curve= 0 ,0
Exp/Cntr=0.3,0.1

Type RM Length L Ch R = 1 ,1402.847,333.27,516.06,547.76
XS GIS Cut Line= 6
     3202285.826    13824605.894      3202566.34    13825272.666
     3202568.187    13825313.066     3202568.231    13825365.564
     3202567.198    13825395.439     3202567.439    13826262.124
#Sta/Elev= 30
 4181.24   24.82 4223.98   25.93 4514.72   26.25 4588.42   25.69  4691.9   23.33
 4741.82   24.46 4801.96   24.61 4828.08   26.11  4892.6   26.24 4942.12   25.58
 4973.75   21.53 4993.97   11.45 5005.76   11.35 5015.95   16.48  5029.6   21.54
 5058.58   25.35 5156.14   24.82 5266.14   26.05 5414.52   25.86  5559.5   25.86
 5588.54   23.76 5602.94   25.52  5628.6   28.64  5673.7   27.84 5694.56   25.76
 5783.46   26.33 5793.48   28.48 5818.52   45.62 5853.24   47.47 5894.12   47.53
#Mann= 6 ,-1 , 0
 4181.24     .07       0 4942.12     .07       0 4973.75    .015       0
  5029.6     .07       0 5414.52     .12       0 5602.94     .07       0
Bank Sta=4973.75,5029.6
XS Rating Curve= 0 ,0
Exp/Cntr=0.3,0.1

Type RM Length L Ch R = 1 ,886.787 ,85.72,84.17,99.39
XS GIS Cut Line= 6
     3202084.219    13824669.583     3202052.048    13825248.655
     3202052.514    13825317.768      3202053.02    13825373.112
     3202053.794    13825404.413     3202024.305    13826393.743
#Sta/Elev= 30
 4325.32   26.27 4585.94   25.54  4845.8    25.5 4928.24   25.01 4943.18   24.34
 4958.44   22.62 4962.92    22.6 4973.75   21.53 4995.29    10.7 5004.12    10.7
 5026.25   21.54 5058.44   23.44 5082.62    24.1  5181.4   24.76 5299.42   24.57
  5445.3   24.86 5561.12   25.53 5746.48   24.76 5758.56   23.64 5782.82   20.34
  5801.6   23.16 5818.58   27.14 5840.24   27.51 5865.54   22.82    5902   26.32
 5983.66   27.66 5998.66   33.98 6013.66   46.06 6024.36   49.23 6050.84   50.08
#Mann= 4 ,-1 , 0
 4325.32     .15       0 4928.24     .07       0 4973.75    .015       0
 5026.25     .07       0
#Block Obstruct= 1 ,-1
 5710.81 5995.22   24.74
Bank Sta=4973.75,5026.25
XS Rating Curve= 0 ,0
Exp/Cntr=0.5,0.3

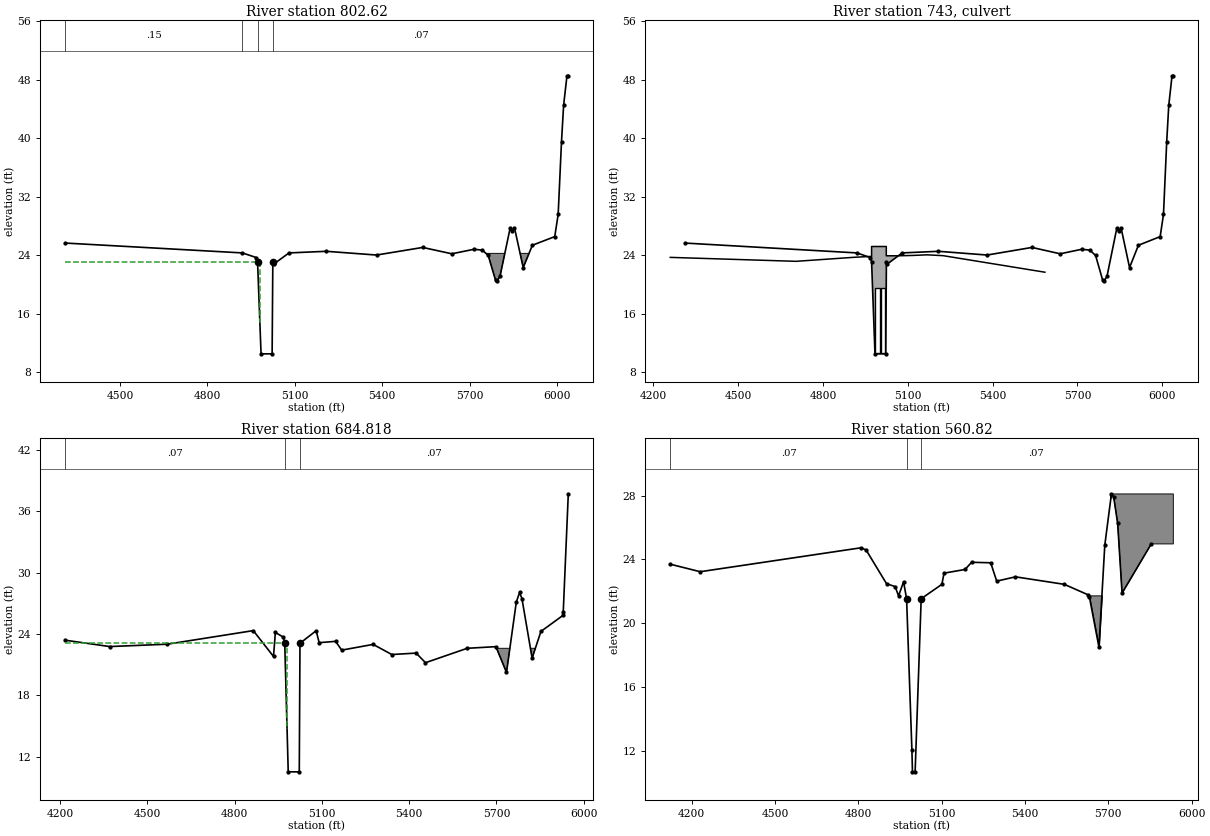
Type RM Length L Ch R = 1 ,802.62  ,85.72,117.8,109.99
XS GIS Cut Line= 6
     3202004.342    13824665.145     3201972.033    13825246.704
     3201972.516    13825318.403     3201973.029    13825374.466
     3201973.764    13825404.209      3201944.34    13826391.359
#Sta/Elev= 30
4311.559   25.664919.989   24.314967.259   23.684971.972   23.12    4984    10.5
    5022    10.55024.391   23.08 5028.03    22.85080.009   24.315208.139   24.53
 5380.52   24.02 5539.14   25.06  5639.1   24.19 5715.42   24.81 5743.92   24.69
5764.241   23.96 5789.38   20.56 5794.26   20.465804.541    21.15839.279   27.69
 5845.74   27.255854.281   27.75  5884.3   22.315915.701   25.365992.581   26.54
6004.338   29.586015.779   39.54 6023.04   44.51 6034.36   48.486039.121   48.55
#Mann= 4 ,-1 , 0
4311.559     .15       04919.989     .07       04971.972    .015       0
5024.391     .07       0
#XS Ineff= 2 , 0
       0    4980   23.125024.391       0   23.08
Permanent Ineff=
       F       F
#Block Obstruct= 1 ,-1
 5724.46 5979.29   24.25
Bank Sta=4971.972,5024.391
XS Rating Curve= 0 ,0
Exp/Cntr=0.5,0.3

Type RM Length L Ch R = 2 ,743     ,,,
BEGIN DESCRIPTION:
2 Box Culverts @ Luella Road
END DESCRIPTION:
Bridge Culvert--1,0,-1,-1, 0
Deck Dist Width WeirC Skew NumUp NumDn MinLoCord MaxHiCord MaxSubmerge Is_Ogee
4,92,2.6,0, 13, 10, , , 0.95, 0, 0,0,,
    42604704.999    4908    4963    4972    4972    5024    5024    5066    5117
5168.001    52255584.999
    23.7   23.16  23.706   23.82   23.82   25.19   25.19  23.918  23.918  23.963
  24.049  23.934   21.67
       0       0       0       0       0       0       0       0       0       0
       0       0       0
    42604704.999    4908    4963    5014    5066    51175168.001    52255584.999
    23.7   23.16  23.706   23.82  23.793  23.918  23.963  24.049  23.934   21.67
       0       0       0       0       0       0       0       0       0       0
Multiple Barrel Culv=2,9,16.5,92,0.012,0.5,1,11,3,10.55,10.55, 2,Culvert #1  , 0 ,4
 4993.75 4993.75 5012.25 5012.25
Culvert Bottom n=0.012
BC Design=,, 0 ,, 0 ,,,,,,
BC HTab HWMax=48.55
BC Use User HTab Curves=0
BC User HTab FreeFlow(D)= 0

Type RM Length L Ch R = 1 ,684.818 ,85.72,124,116.67
XS GIS Cut Line= 6
     3201924.465    13824660.708     3201892.018    13825244.753
     3201892.518    13825319.038     3201893.038     13825375.82
     3201893.735    13825404.006     3201864.376    13826388.976
#Sta/Elev= 30
4217.351   23.384369.991   22.764568.069   22.994863.891   24.324933.369   21.79
 4939.78   24.144967.259   23.684971.971   23.12    4984    10.5    5022    10.5
5024.391   23.085080.009   24.315090.351   23.145146.881   23.27 5167.84   22.41
 5275.89   22.97 5340.26   21.98  5423.8   22.12 5455.96   21.18 5599.43   22.59
 5698.07   22.75 5734.49   20.235768.251   27.125779.509   28.05 5787.58   27.45
5822.571   21.63 5852.88   24.245928.202    25.8 5929.58   26.135946.971   37.71
#Mann= 3 ,-1 , 0
4217.351     .07       04971.971    .015       05024.391     .07       0
#XS Ineff= 2 , 0
       0    4980   23.125024.391       0   23.08
Permanent Ineff=
       F       F
#Block Obstruct= 1 ,-1
 5680.55 5926.28   22.59
Bank Sta=4971.971,5024.391
XS Rating Curve= 0 ,0
Exp/Cntr=0.5,0.3

Type RM Length L Ch R = 1 ,560.82  ,798.46,560.82,280.5
XS GIS Cut Line= 6
     3201844.588     13824656.27     3201812.003    13825242.801
     3201812.521    13825319.674     3201813.047    13825377.175
     3201813.705    13825403.802     3201784.411    13826386.592
#Sta/Elev= 30
  4122.9    23.7 4230.66   23.23 4810.32   24.73 4827.98   24.59 4901.54   22.48
  4932.3    22.3 4944.84   21.72 4962.92    22.6 4973.75   21.53 4992.83   12.08
 4994.87    10.7 5004.44    10.7 5026.25   21.54  5100.8   22.44 5108.46   23.14
 5184.04   23.37  5207.8   23.82 5276.54   23.79 5298.14   22.64  5365.8   22.91
 5541.52   22.44 5626.34   21.79  5631.7   21.67 5666.28   18.51  5687.3   24.89
 5711.28   28.11 5719.52   27.89  5733.7   26.25 5749.54   21.89 5854.58   24.97
#Mann= 3 ,-1 , 0
  4122.9     .07       0 4973.75    .015       0 5026.25     .07       0
#Block Obstruct= 2 ,-1
 5597.27 5695.11   21.75 5708.76 5934.02    28.1
Bank Sta=4973.75,5026.25
XS Rating Curve= 0 ,0
Exp/Cntr=0.3,0.1

Chan Stop Cuts=-1
Use User Specified Reach Order=0
Composite Channel Slope=5